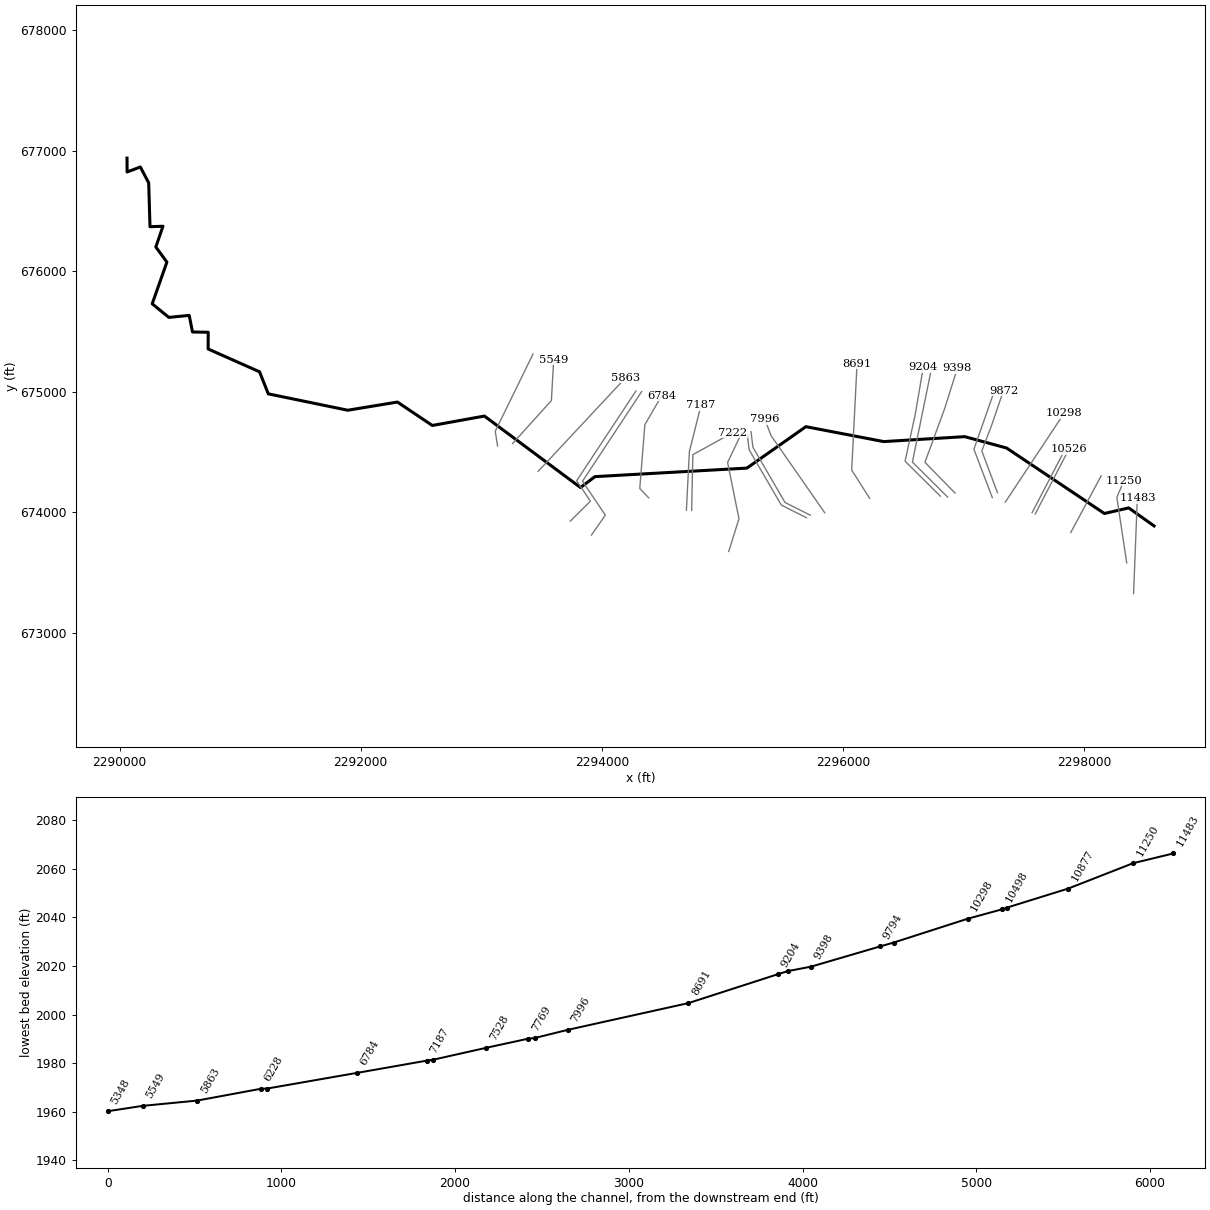
--- DODSONRN.prj (project) ---

Proj Title=DODSONRN
Current Plan=p01
Default Exp/Contr=0,0
English Units
Geom File=g01
Flow File=f01
Plan File=p01
Background Map Layer=Inundation Boundary (P100yr Value_0)
BEGIN DESCRIPTION:
----------MODEL BY WOOD PLC 2022----------
AFH study
Randolph County, WV
HEC-RAS Version: RAS 6.2
Vertical Datum: NAVD88
Projection: NAD 1983 StatePlane West Virginia S FIPS 4702 (US Feet)
Terrain: 1-meter LIDAR (FEMA Region III 3DEP collected 2016-2018)
Land Use: 2019 NLCD
Hydrologic Method:
WV SIR2010-5033 regression equations
Additional Model Notes:
None
END DESCRIPTION:
DSS Export Rating Curves= 0
DSS Export Rating Curve Sorted= 0
DSS Export Volume Flow Curves= 0
DXF OffsetX= 0
DXF OffsetY= 0
DXF ScaleX= 0
DXF ScaleY= 0

--- DODSONRN.p01 (plan) ---

Plan Title=Floodplain
Program Version=6.20
Short Identifier=Floodplain
Geom File=g01
Flow File=f01
Subcritical Flow
K Sum by GR= 0
Std Step Tol= 0.01
Critical Tol= 0.01
Num of Std Step Trials= 20
Max Error Tol= 0.3
Flow Tol Ratio= 0.001
Split Flow NTrial= 30
Split Flow Tol= 0.02
Split Flow Ratio= 0.02
Log Output Level= 0
Friction Slope Method= 1
Unsteady Friction Slope Method= 2
Unsteady Bridges Friction Slope Method= 1
Parabolic Critical Depth
Global Vel Dist= 0 , 0 , 0
Global Log Level= 0
CheckData=True
Encroach Param=-1 ,0,0, 0
Mapping Interval=1HOUR
Computation Time Step Use Courant=        0
Computation Time Step Use Time Series=    0
Computation Time Step Count To Double=0
Computation Time Step Max Doubling=0
Computation Time Step Max Halving=0
Computation Time Step Residence Courant=0
Run HTab= 0
Run UNet= 0
Run Sediment= 0
Run PostProcess= 0
Run WQNet= 0
Run RASMapper=-1
UNET Theta= 0
UNET Theta Warmup= 0
UNET ZTol= 0
UNET ZSATol= 0
UNET MxIter= 0
UNET Max Iter WO Improvement= 0
UNET MaxInSteps= 0
UNET DtIC= 0
UNET DtMin= 0
UNET MaxCRTS= 0
UNET WFStab= 0
UNET SFStab= 0
UNET WFX= 1
UNET SFX= 1
UNET Gravity=32.174
UNET 1D Methodology=Finite Difference
UNET DSS MLevel= 1
UNET Pardiso=0
UNET DZMax Abort= 0
UNET Use Existing IB Tables= 0
UNET Froude Reduction=False
UNET Froude Limit= 0
UNET Froude Power= 0
UNET D1 Cores= 0
UNET WindReference=Eulerian
UNET WindDragFormulation=Hsu (1988)
UNET D2 Coriolis=0
UNET D2 Cores= 0
UNET D2 Theta= 1
UNET D2 Theta Warmup= 1
UNET D2 Z Tol= 0.01
UNET D2 Volume Tol= 0.01
UNET D2 Max Iterations= 20
UNET D2 Equation= 0
UNET D2 RampUpFraction=0.1
UNET D2 TimeSlices= 1
UNET D2 Turbulence Formulation=Non-Conservative (original)
UNET D2 Eddy Viscosity=0.3
UNET D2 Transverse Eddy Viscosity=0.1
UNET D2 Smagorinsky Mixing=0
UNET D2 BCVolumeCheck=0
UNET D2 Cores=0
UNET D2 SolverType=PARDISO (Direct)
UNET D2 Minimum Iterations= 2147483647
UNET D2 Maximum Iterations= 2147483647
UNET D2 Restart Number= 10
UNET D2 Relaxation Coeff=1.3
UNET D2 SOR Precondition Iterations= 10
UNET D2 ILUT Maximum Fill= 8
UNET D2 ILUT Tolerance=1E-08
UNET D1D2 MaxIter= 0
UNET D1D2 ZTol=0.01
UNET D1D2 QTol=0.1
UNET D1D2 MinQTol=1
Write IC File= 0
Write IC File at Fixed DateTime=0
Write IC File at Sim End=0
Echo Input=False
Echo Parameters=False
Echo Output=False
Write Detailed= 0
HDF Write Warmup=0
HDF Write Time Slices=0
HDF Flush=0
HDF Compression= 1
HDF Chunk Size= 1
HDF Spatial Parts= 1
HDF Use Max Rows=0
HDF Fixed Rows= 1
Calibration Method= 0
Calibration Iterations= 20
Calibration Max Change=0.05
Calibration Tolerance=0.2
Calibration Maximum=1.5
Calibration Minimum=0.5
Calibration Optimization Method= 1
WQ AD Non Conservative
WQ ULTIMATE=-1
WQ Max Comp Step=1HOUR
WQ Output Interval=15MIN
WQ Output Selected Increments= 0
WQ Output face flow=0
WQ Output face velocity=0
WQ Output face area=0
WQ Output face dispersion=0
WQ Output cell volume=0
WQ Output cell surface area=0
WQ Output cell continuity=0
WQ Output cumulative cell continuity=0
WQ Output face conc=0
WQ Output face dconc_dx=0
WQ Output face courant=0
WQ Output face peclet=0
WQ Output face adv mass=0
WQ Output face disp mass=0
WQ Output cell mass=0
WQ Output cell source sink temp=0
WQ Output nsm pathways=0
WQ Output nsm derived pathways=0
WQ Create Restart=0
WQ Fixed Restart=0
WQ System Summary=0
WQ Write To DSS=0
Sorting and Armoring Iterations= 10
XS Update Threshold= 0.02
Bed Roughness Predictor= 0
Hydraulics Update Threshold= 0.02
Energy Slope Method= 1
Volume Change Method= 1
Sediment Retention Method= 0
Sediment TS Multiplier= 1
Warm Up Method= 0
XS Weighting Method= 0
Number of US Weighted Cross Sections= 1
Number of DS Weighted Cross Sections= 1
Upstream XS Weight=0
Main XS Weight=1
Downstream XS Weight=0
Number of DS XS's Weighted with US Boundary= 1
Upstream Boundary Weight= 1
Weight of XSs Associated with US Boundary= 0
Number of US XS's Weighted with DS Boundary= 1
Downstream Boundary Weight= 0.5
Weight of XSs Associated with DS Boundary= 0.5
Percentile Method= 0
Sediment Output Level= 3
Mass or Volume Output= 0
Output Increment Type= 1
Profile and TS Output Increment= 1
Transport Output Increment 1
XS Output Flag= 0
XS Output Increment= 10
Read HDF5 Sediment Hotstart= 0
Sediment Hotstart Type= 0
Write Gradation File= 0
Read Gradation Hotstart= 0
Write HDF5 File= 1
Write Binary Output= 1
Write DSS Sediment File= 0
DSS Sediment Output Type= 1
SV Curve= 0
Specific Gage Flag= 0
Subcell Erosion Methods= 0
Subcell Deposition Methods= 0
Advection Scheme= 1
Matrix Solver= 0
Implicit Weighting Factor= 1
Maximum Outer Loop Convergence Iterations= 5
Convergence Maximum Absolute= 0.001
Convergence RMSE= 0.0001
Grain Fractions Max Abs Error= 0.001
Max Subgrid Regions= 1
Max Subgrid Length Scale= 3.402823E+38
Initial Layer Thickness= 3.402823E+38
Min Layer Thickness= 3.402823E+38
Max Layer Thickness= 3.402823E+38
Number of Layers= 5

--- DODSONRN.f01 (steady flow) ---

Flow Title=Flow
Program Version=6.20
Number of Profiles= 1
Profile Names=P100yr
River Rch & RM=DODSONRN,Main,11483
     378
River Rch & RM=DODSONRN,Main,6784
     449
River Rch & RM=DODSONRN,Main,6228
     573
River Rch & RM=DODSONRN,Main,3579
     639
Boundary for River Rch & Prof#=DODSONRN,Main            , 1
Up Type= 0
Dn Type= 3
Dn Slope=0.00085
DSS Import GetInterval= 0
DSS Import GetPeak= 0
DSS Import FillOption= 0

--- DODSONRN.g01 (geometry) ---

Geom Title=Geometry
Program Version=6.20

River Reach=DODSONRN        ,Main
Reach XY= 30
     2298577.889      673887.213     2298367.472      674036.866
     2298166.083      673990.338     2297354.969      674533.761
     2297008.138      674627.971     2296336.151      674587.015
     2295690.865      674710.743     2295201.974      674367.041
     2293942.049      674296.208     2293822.332      674205.773
     2293025.564      674798.765     2292593.438      674720.743
     2292304.108      674915.067     2291892.603      674847.134
     2291233.669      674983.042     2291160.993      675166.002
     2290734.561       675355.43     2290735.608      675494.261
     2290605.201      675496.188     2290577.815      675633.986
      2290408.97      675617.471      2290271.02      675730.332
     2290392.877      676076.397      2290301.07      676201.613
     2290360.119      676373.653     2290252.684      676370.017
     2290241.937      676733.584     2290172.614      676865.516
     2290062.896      676823.772     2290062.181      676939.112

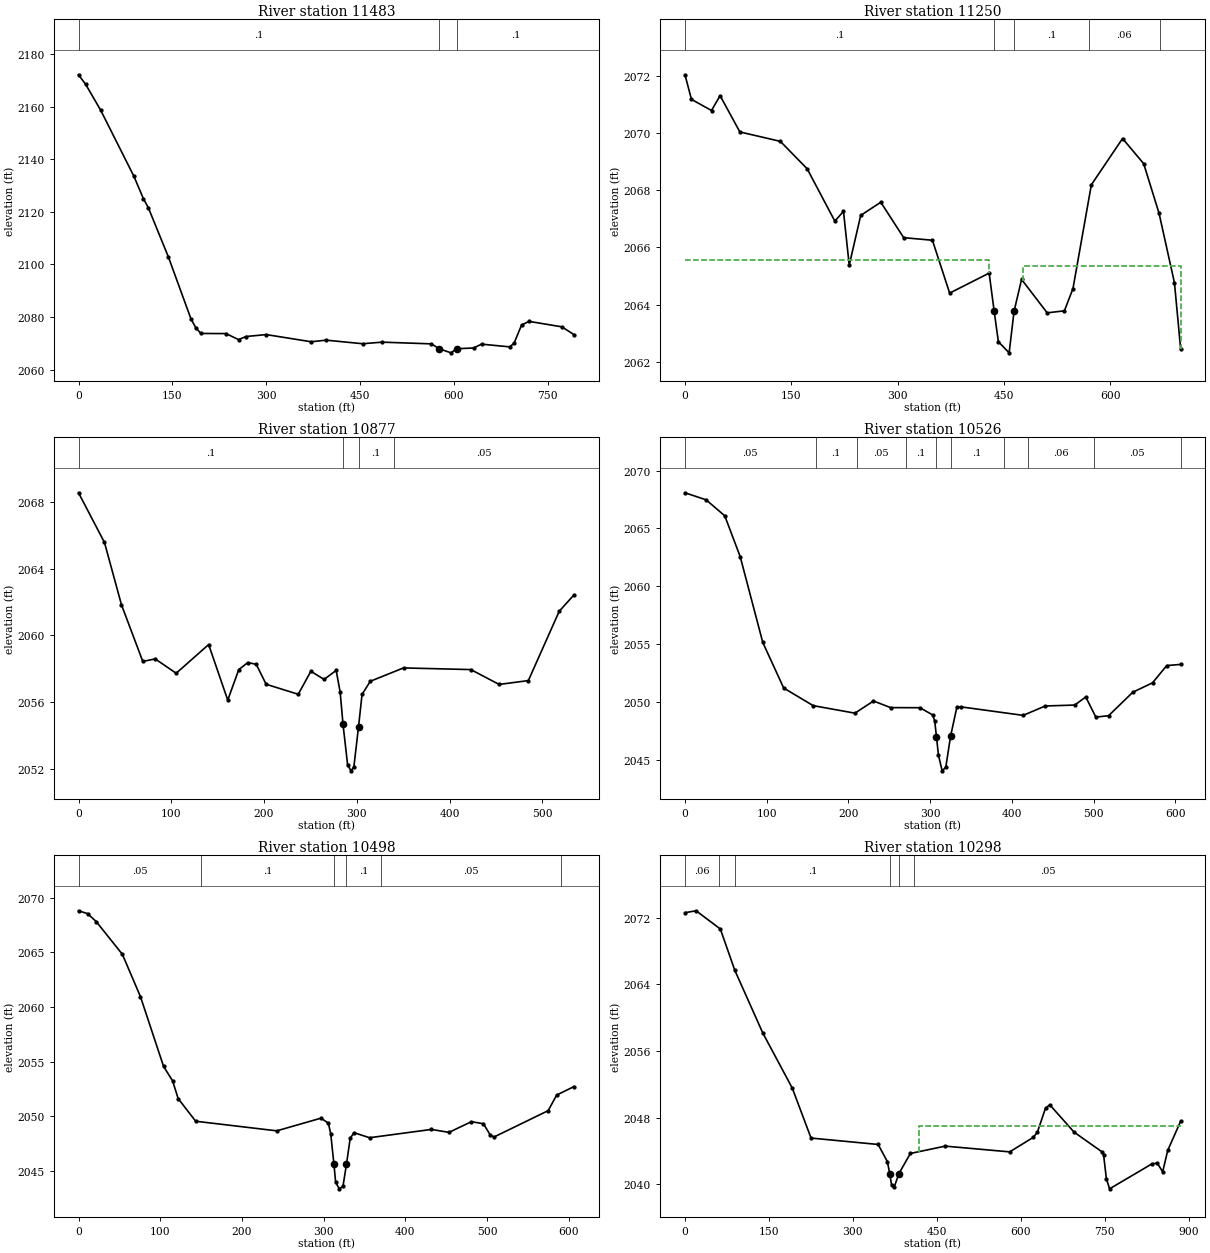
Type RM Length L Ch R = 1 ,11483   ,221.2,232.6,230.9
XS GIS Cut Line= 2
2298407.93016974673325.7008641132298439.20152408674117.087484508
#Sta/Elev= 30
       0 2172.25    11.5 2168.58    35.5 2158.72    88.3  2133.7   103.7 2125.06
   111.6  2121.6   143.6 2102.88   179.6 2079.34   187.6 2075.83   195.6 2073.73
   235.7 2073.68   255.7 2071.39   267.7 2072.57   300.1  2073.3   371.8 2070.57
   395.8 2071.18   454.1 2069.82     485 2070.42   563.9 2069.77   576.72067.877
   595.2 2066.35     6042067.905   631.3  2068.2     644 2069.66   689.1 2068.62
     696 2070.03     708 2076.97     720 2078.33   772.1 2076.26     792 2073.26
#Mann= 3 ,-1,0
       0      .1       0   576.7    .045       0     604      .1       0
Bank Sta=576.7,604
XS Rating Curve= 0 ,0
Exp/Cntr(USF)=0,0
Exp/Cntr=0.3,0.1

Type RM Length L Ch R = 1 ,11250   ,373.7,372.9,365
XS GIS Cut Line= 3
2298351.28668992673580.1923060562298269.35864256674123.438281629
2298327.43114045674261.214627683
#Sta/Elev= 30
       0 2072.04     9.1 2071.18    37.4 2070.79    49.5 2071.31    77.4 2070.04
   134.5 2069.71   172.3 2068.75   211.3 2066.92   223.5 2067.26   231.6 2065.38
   247.8 2067.12   276.1 2067.58   308.4 2066.34   348.9 2066.25   373.2  2064.4
   428.9  2065.1   435.9 2063.78   441.9  2062.7   457.1 2062.31     464 2063.76
   474.6 2064.88   510.7 2063.71     535 2063.78   547.1 2064.56     573 2068.19
     617 2069.81   646.8 2068.93   668.5 2067.19   690.2 2064.76   698.9 2062.45
#Mann= 5 ,-1,0
       0      .1       0   435.9    .045       0     464      .1       0
  569.39     .06       0  669.39      .1       0
#XS Ineff= 2 , 0
          428.42 2065.55  476.87         2065.36
Permanent Ineff=
       F       F
Bank Sta=435.9,464
XS Rating Curve= 0 ,0
Exp/Cntr(USF)=0,0
Exp/Cntr=0.3,0.1

Type RM Length L Ch R = 1 ,10877   ,350.2,351.3,350.6
XS GIS Cut Line= 2
2297887.16152128673832.3212973992298139.51045007674303.433857456
#Sta/Elev= 30
       0 2068.55      28 2065.57    46.3 2061.84    69.3 2058.44    82.7 2058.59
   105.3 2057.73   140.3 2059.45   160.9 2056.12   172.8 2057.95   182.5 2058.37
   191.6 2058.27   202.3 2057.07   236.9 2056.47   250.5 2057.85   264.8 2057.36
   277.8  2057.9   282.1  2056.6   285.2 2054.66   290.2 2052.21   293.9 2051.88
   296.9 2052.12   301.9 2054.52   305.7 2056.46   314.6 2057.25   350.4 2058.05
     423 2057.95   453.5 2057.06     485 2057.29   518.3 2061.45   534.4 2062.44
#Mann= 4 ,-1,0
       0      .1       0   285.2    .045       0   301.9      .1       0
     340     .05       0
Bank Sta=285.2,301.9
XS Rating Curve= 0 ,0
Exp/Cntr(USF)=0,0
Exp/Cntr=0.3,0.1

Type RM Length L Ch R = 1 ,10526   ,28.1,28.1,28
XS GIS Cut Line= 2
  2297592.248403673985.9811831362297872.06419552674524.185432716
#Sta/Elev= 30
       0 2068.08    25.9 2067.47    48.7 2066.09    67.6 2062.56    95.2 2055.16
   120.8 2051.22   156.9  2049.7     208 2049.05   230.7  2050.1   251.6 2049.53
   287.6 2049.52   303.3 2048.89   305.7 2048.34   307.8 2046.99   310.2 2045.45
   314.7 2044.07   319.2 2044.38     3252047.045   332.7 2049.55   337.2  2049.6
   413.9 2048.86   440.9 2049.67     477 2049.75   490.5 2050.45   502.8 2048.71
   518.4 2048.83   548.1 2050.86   572.2 2051.67   589.6 2053.16   606.6 2053.26
#Mann= 10 ,-1,0
       0     .05       0     160      .1       0     210     .05       0
     270      .1       0   307.8    .045       0     325      .1       0
     390     .05       0     420     .06       0     500     .05       0
   606.6      .1       0
Bank Sta=307.8,325
XS Rating Curve= 0 ,0
Exp/Cntr(USF)=0,0
Exp/Cntr=0.3,0.1

Type RM Length L Ch R = 1 ,10498   ,201,200.2,199.4
XS GIS Cut Line= 2
2297567.03977304673997.9552823662297846.85556556674536.159531945
#Sta/Elev= 30
       0 2068.82    11.1 2068.56    21.7 2067.83    53.7 2064.83    75.8 2060.96
   104.1 2054.57   115.2 2053.24   121.9 2051.63   143.4 2049.55   242.6 2048.67
   296.7 2049.83   305.8 2049.37   308.7 2048.39   312.62045.607   314.7 2043.95
   319.2 2043.36   323.7 2043.61   327.92045.594   332.5 2047.99   337.2  2048.5
   356.2 2048.04   431.9  2048.8   453.4 2048.53   480.8 2049.51   495.6 2049.32
   504.1 2048.26   508.6 2048.11   574.8 2050.52   585.2 2051.95   606.6 2052.73
#Mann= 6 ,-1,0
       0     .05       0     150      .1       0   312.6    .045       0
   327.9      .1       0     370     .05       0     590      .1       0
Bank Sta=312.6,327.9
XS Rating Curve= 0 ,0
Exp/Cntr(USF)=0,0
Exp/Cntr=0.3,0.1

Type RM Length L Ch R = 1 ,10298   ,423.9,425.6,426.7
XS GIS Cut Line= 2
2297344.54016314674085.2915794132297833.44454918674823.986286984
#Sta/Elev= 30
       0 2072.61    19.9 2072.84    63.2 2070.65    89.1 2065.68     139 2058.17
   191.7 2051.55   225.3 2045.54   345.2 2044.77   361.7 2042.71   366.12041.216
   369.2  2039.9     374 2039.66   382.32041.266   402.8 2043.69   465.1 2044.57
   580.3 2043.88   622.6 2045.63   629.9 2046.26   644.4 2049.15     652 2049.53
   695.4 2046.25   745.8 2043.86   748.2 2043.47   753.1 2040.66   758.8 2039.44
   834.5 2042.44   844.1 2042.53   853.7 2041.48   862.7 2044.05   885.8 2047.56
#Mann= 6 ,-1,0
       0     .06       0      60     .05       0      90      .1       0
   365.8    .045       0     382      .1       0     410     .05       0
#XS Ineff= 2 , 0
                          418.94         2046.95
Permanent Ineff=
       F       F
Bank Sta=366.1,382.3
XS Rating Curve= 0 ,0
Exp/Cntr(USF)=0,0
Exp/Cntr=0.3,0.1

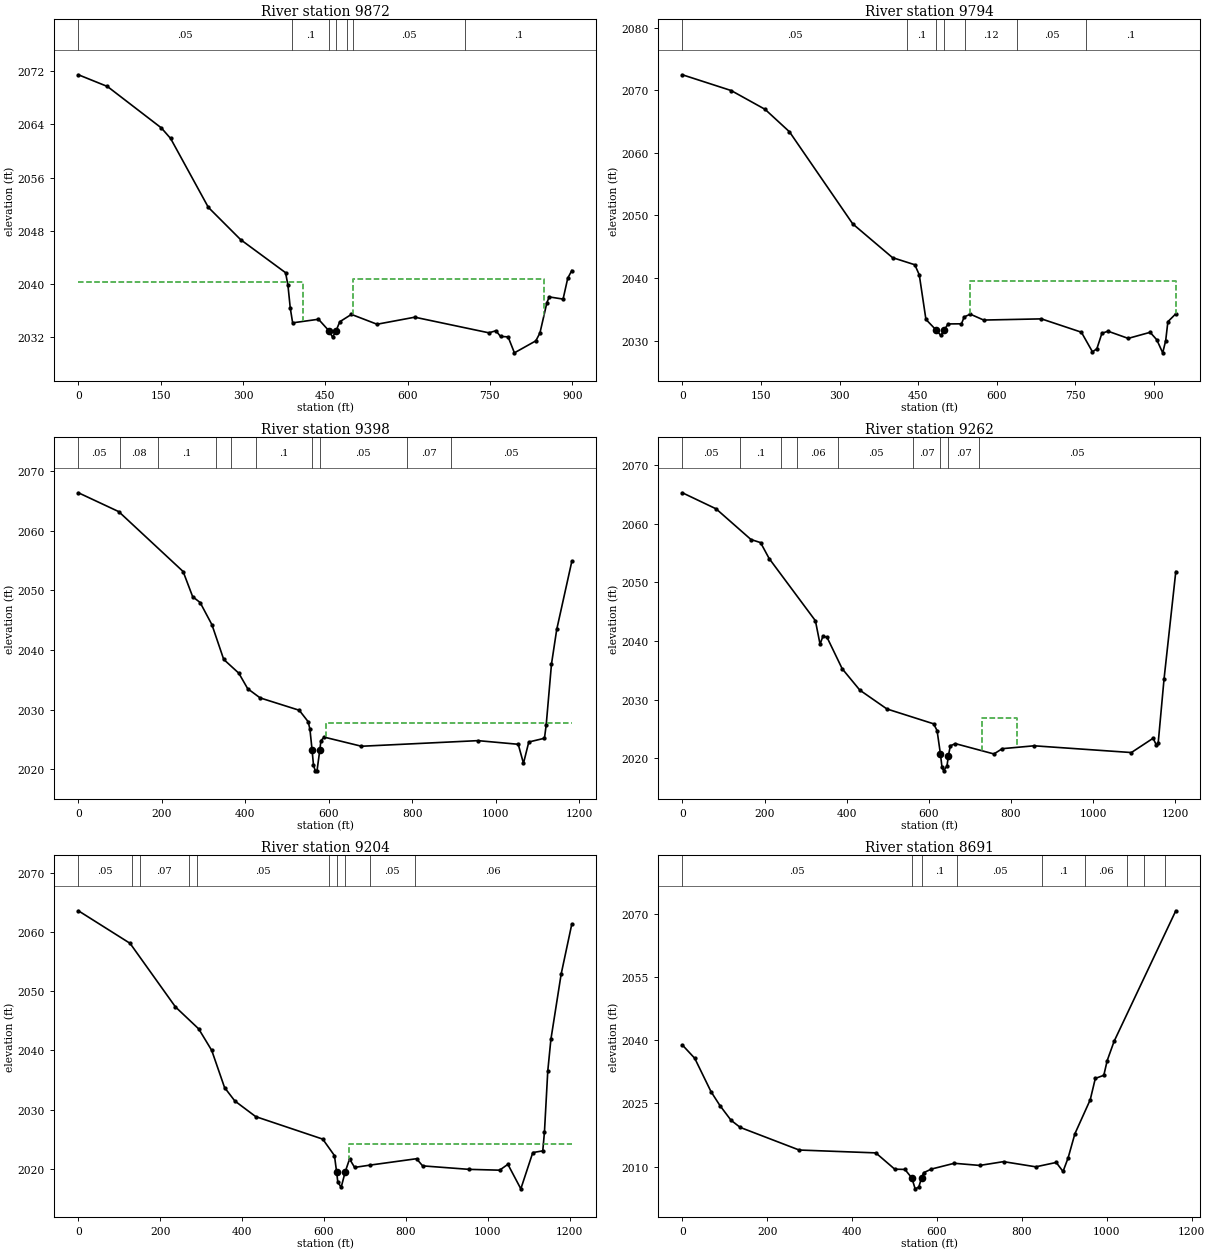
Type RM Length L Ch R = 1 ,9872    ,80.7,78.4,79.3
XS GIS Cut Line= 4
2297279.32720533  674163.64234882297149.56526616674509.703660894
2297230.22471293674719.7661376262297328.46204804675008.176892115
#Sta/Elev= 30
       0 2071.45    52.9 2069.69   151.2 2063.46   168.1 2061.87   236.8 2051.52
   295.7 2046.66   377.6 2041.69   381.9 2039.82   386.2 2036.34   390.5 2034.15
   437.6 2034.69     4572032.921   463.3 2031.99   469.62032.973   476.5 2034.32
   497.6 2035.42   544.3 2033.94   613.1    2035   748.2 2032.65   760.9 2032.96
   769.4 2032.11   783.2 2032.04   794.7 2029.64   833.7 2031.44   841.2 2032.62
   853.9 2037.18   858.1 2038.05   883.4 2037.72   891.9 2040.86   899.3 2042.02
#Mann= 7 ,-1,0
       0     .05       0  389.59      .1       0     457    .045       0
   469.6      .1       0  489.59     .12       0  499.59     .05       0
  704.61      .1       0
#XS Ineff= 2 ,-1
       0   409.3  2040.3     501   848.1 2040.67
Permanent Ineff=
       F       F
Bank Sta=457,469.6
XS Rating Curve= 0 ,0
Exp/Cntr(USF)=0,0
Exp/Cntr=0.3,0.1

Type RM Length L Ch R = 1 ,9794    ,392.9,396.1,393.4
XS GIS Cut Line= 4
2297236.65854334674122.1240058062297084.20883721674523.770346954
2297163.96071115674750.4335636532297253.72236357675007.380327315
#Sta/Elev= 30
       0 2072.49    93.1 2069.97   157.8 2066.97   204.4 2063.38   325.3 2048.65
   401.2 2043.26   443.8 2042.12   452.3 2040.51     465 2033.38   484.42031.697
   493.4 2030.82   500.22031.758   507.4 2032.66   532.9 2032.68     538 2033.78
   549.8 2034.22   575.3 2033.28   685.5 2033.47   761.8 2031.34     783  2028.2
   791.4 2028.69     801 2031.16   812.6  2031.5   851.2 2030.35   893.1 2031.32
   905.8 2030.13   917.1 2028.04   922.8 2029.99     927 2033.02   942.1 2034.28
#Mann= 7 ,-1,0
       0     .05       0  429.61      .1       0   484.4    .045       0
   500.2      .1       0  539.61     .12       0  639.61     .05       0
  769.89      .1       0
#XS Ineff= 2 , 0
                          548.84         2039.55
Permanent Ineff=
       F       F
Bank Sta=484.4,500.2
XS Rating Curve= 0 ,0
Exp/Cntr(USF)=0,0
Exp/Cntr=0.3,0.1

Type RM Length L Ch R = 1 ,9398    ,133.5,135.3,136.2
XS GIS Cut Line= 4
2296927.48408843674160.0228162542296678.28745341674415.082901507
2296841.75534519674861.3791992552296946.99717485675195.582314295
#Sta/Elev= 30
       0 2066.33    96.7 2063.17   250.9 2053.14   273.8 2048.92   291.7 2047.94
     320 2044.22   348.2 2038.41   384.4  2036.1   405.7  2033.5   435.5 2031.96
   529.2 2029.89   550.5 2027.98   554.8 2026.72     5602023.187   563.3 2020.71
   567.6 2019.74   571.8 2019.76   578.52023.246   581.1 2024.79   588.9 2025.39
   678.3 2023.86   957.5  2024.8  1053.9 2024.19  1066.5    2021  1079.2 2024.57
  1116.8  2025.2    1121 2027.47  1133.6 2037.63  1146.2 2043.44  1182.3 2054.83
#Mann= 10 ,-1,0
       0     .05       0     100     .08       0     190      .1       0
     330     .06       0  366.59     .07       0  426.59      .1       0
     560    .045       0   578.5     .05       0  786.59     .07       0
  891.88     .05       0
#XS Ineff= 2 , 0
                          592.35         2027.76
Permanent Ineff=
       F       F
Bank Sta=560,578.5
XS Rating Curve= 0 ,0
Exp/Cntr(USF)=0,0
Exp/Cntr=0.3,0.1

Type RM Length L Ch R = 1 ,9262    ,58.2,58.4,57.9
XS GIS Cut Line= 3
2296866.22568874674127.1269919952296574.13791524674416.840068144
  2296731.920447675191.189417896
#Sta/Elev= 30
       0  2065.3    82.1 2062.56     167 2057.33   190.4  2056.8   211.3 2054.09
     324 2043.47   335.3 2039.47   342.3 2040.85   352.2 2040.66   389.2 2035.29
   432.2 2031.64   498.2 2028.43   611.8  2025.9   620.3 2024.75   628.62020.683
   632.2 2018.53   636.3 2017.88   644.4 2018.71     6482020.492   652.6 2022.15
   664.8 2022.52   758.7 2020.76   779.1 2021.66   856.7 2022.15  1093.5    2021
  1146.5 2023.44  1154.7 2022.21  1158.8 2022.61    1173 2033.49  1201.7 2051.86
#Mann= 9 ,-1,0
       0     .05       0     140      .1       0     240     .07       0
     280     .06       0     380     .05       0   561.4     .07       0
   628.5    .045       0   647.9     .07       0   721.4     .05       0
#XS Ineff= 1 ,-1
  729.79   815.7 2026.85
Permanent Ineff=
       F
Bank Sta=628.6,648
XS Rating Curve= 0 ,0
Exp/Cntr(USF)=0,0
Exp/Cntr=0.3,0.1

Type RM Length L Ch R = 1 ,9204    ,511.5,513.1,514.3
XS GIS Cut Line= 4
2296805.67090643674134.2510840322296513.58313293 674423.96416018
2296597.59086003674812.6594651832296664.29540952675203.027441153
#Sta/Elev= 30
       0 2063.66   126.1 2058.15     237 2047.38   293.8 2043.66   325.6 2040.02
     357 2033.72   382.1 2031.45   433.1  2028.8   596.8 2024.99   625.4  2022.2
   630.72019.407   633.6 2017.71   641.8 2016.83   651.82019.478   662.3 2021.63
   674.6  2020.2   711.4 2020.58   825.8 2021.67   840.8 2020.46   953.9 2019.87
  1028.7 2019.73    1049 2020.72  1080.6 2016.57  1109.8 2022.71  1134.2    2023
  1138.3  2026.2  1146.4 2036.51    1154 2041.87  1179.1 2052.94  1205.1 2061.41
#Mann= 10 ,-1,0
       0     .05       0     130      .1       0     150     .07       0
     270     .06       0     290     .05       0   611.4      .1       0
   630.6    .045       0   651.7      .1       0   711.4     .05       0
   821.4     .06       0
#XS Ineff= 2 , 0
                          660.47         2024.24
Permanent Ineff=
       F       F
Bank Sta=630.7,651.8
XS Rating Curve= 0 ,0
Exp/Cntr(USF)=0,0
Exp/Cntr=0.3,0.1

Type RM Length L Ch R = 1 ,8691    ,686.4,695.1,699.1
XS GIS Cut Line= 3
2296219.48802038674116.3573219352296070.69351534674351.050935442
2296115.34046398675234.583468345
#Sta/Elev= 30
       0 2038.88    29.1 2035.73    67.3 2027.83    88.4 2024.51   114.6 2021.01
   136.3 2019.31   275.1 2013.94   455.7 2013.26   500.3 2009.39   524.3 2009.33
   540.6  2007.3   548.4 2004.72     557 2005.14   563.4  2007.3   568.4 2008.55
   586.5 2009.41   640.5 2010.79   700.6 2010.28   756.6 2011.18   832.7 2009.95
   880.8 2010.99   896.8 2008.84   908.8 2012.07   924.8 2017.81   960.9 2025.88
   972.9 2030.95   992.9 2031.69  1000.9 2035.19  1017.1 2039.75  1162.5 2070.77
#Mann= 9 ,-1,0
       0     .05       0   540.6    .045       0   563.4      .1       0
  647.89     .05       0  847.89      .1       0  947.89     .06       0
 1047.89      .1       0 1087.89     .06       0 1137.89      .1       0
Bank Sta=540.6,563.4
XS Rating Curve= 0 ,0
Exp/Cntr(USF)=0,0
Exp/Cntr=0.3,0.1

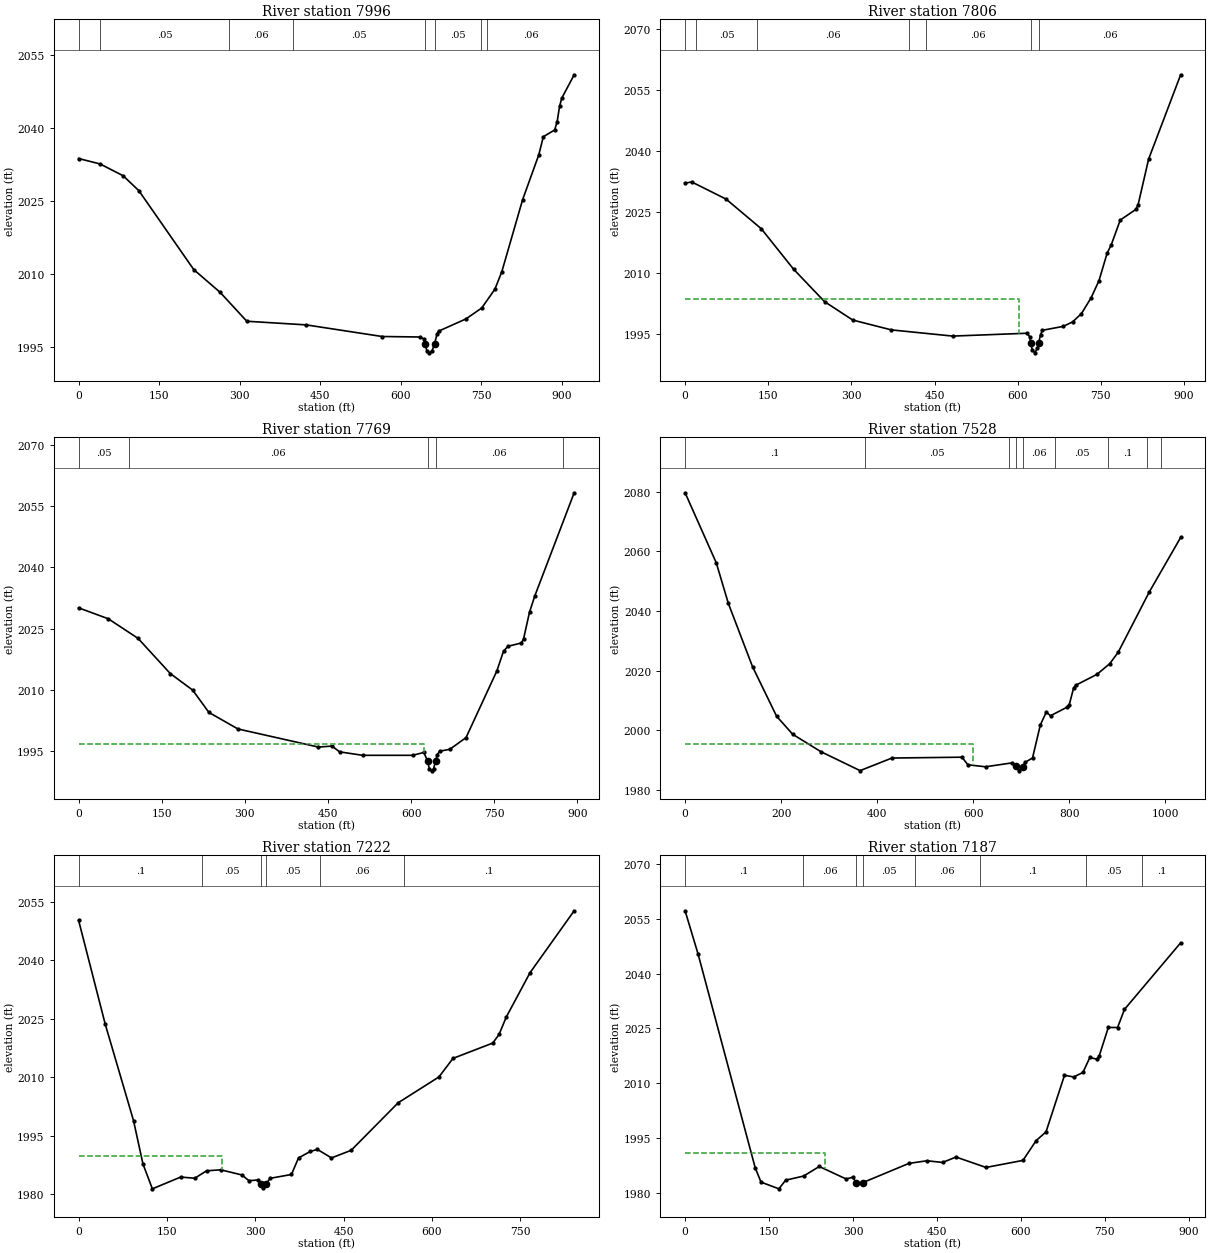
Type RM Length L Ch R = 1 ,7996    ,190.2,189.5,189.1
XS GIS Cut Line= 3
2295847.00288884673997.1917137172295402.54661801674636.071199192
2295350.61198707674770.716538679
#Sta/Elev= 30
       0 2033.68      40 2032.56    82.8 2030.14   112.1 2027.07   214.4 2010.82
   263.5 2006.14   313.1  2000.2   423.9 1999.45   565.1 1997.06   635.3 1996.96
   642.8 1996.56   645.11995.566   648.6 1993.98   652.9  1993.7   657.8 1994.02
   662.61995.516   667.5 1997.67   670.4 1998.17   721.1 2000.68   750.4 2002.92
     775 2006.79     788 2010.43   826.6 2025.21   856.6  2034.4   865.2 2038.17
   886.2 2039.55   890.9 2041.26   895.4 2044.42   899.5  2046.1   922.6 2050.91
#Mann= 8 ,-1,0
       0     .07       0      40     .05       0     280     .06       0
     400     .05       0   645.1    .045       0   662.6     .05       0
     750      .1       0     760     .06       0
Bank Sta=645.1,662.6
XS Rating Curve= 0 ,0
Exp/Cntr(USF)=0,0
Exp/Cntr=0.3,0.1

Type RM Length L Ch R = 1 ,7806    ,37.8,37.7,37.8
XS GIS Cut Line= 4
2295726.92898402673976.7361631642295517.99596372674081.903790828
2295251.57130697674540.4346474432295236.14672158674669.440270711
#Sta/Elev= 30
       0 2032.08      12 2032.36    73.9 2028.15   137.4 2020.87   195.6 2010.93
   251.6 2002.93   302.5  1998.4   372.2 1995.98   482.9 1994.46     617 1995.16
   621.7 1994.33   623.9 1992.72   626.3 1991.07   630.9 1990.34   635.6 1991.44
  637.771992.734   641.4 1994.84   644.8 1995.89   682.4 1996.85   699.3 1997.96
   715.2    2000   732.7 2003.91   746.8  2008.1   761.4 2014.82     769 2016.94
   785.1 2022.99   813.3 2025.61   817.3 2026.73   836.3 2037.97   894.1 2058.72
#Mann= 7 ,-1,0
       0     .06       0      20     .05       0     130     .06       0
  403.91     .05       0  433.91     .06       0   623.9    .045       0
  637.77     .06       0
#XS Ineff= 2 , 0
          602.44 2003.63
Permanent Ineff=
       F       F
Bank Sta=623.9,637.77
XS Rating Curve= 0 ,0
Exp/Cntr(USF)=0,0
Exp/Cntr=0.3,0.1

Type RM Length L Ch R = 1 ,7769    ,243.3,241.1,238.5
XS GIS Cut Line= 4
2295695.95691981673955.0928186552295487.02389952674060.260446319
2295220.59924277674518.7913029342295205.17465738674647.796926202
#Sta/Elev= 30
       0 2030.07    53.5 2027.39   107.2 2022.58   165.4 2013.94   205.8 2009.88
     235 2004.41   287.4 2000.35   432.7  1995.9     457 1996.15   470.9 1994.73
   512.5 1993.88   602.4 1993.88   622.9 1994.58   629.7 1992.41   632.8 1990.53
   637.5 1990.07   640.5 1990.63  644.011992.409   646.7 1993.95   651.3 1994.88
   669.8 1995.36     699 1998.23   754.6 2014.59   766.6 2019.42   774.7 2020.64
   798.9 2021.45   802.7 2022.42   813.5    2029     823 2032.97   894.1 2058.31
#Mann= 5 ,-1,0
       0     .05       0      90     .06       0   629.7    .045       0
  644.01     .06       0  874.22      .1       0
#XS Ineff= 2 , 0
          622.95 1996.72
Permanent Ineff=
       F       F
Bank Sta=629.7,644.01
XS Rating Curve= 0 ,0
Exp/Cntr(USF)=0,0
Exp/Cntr=0.3,0.1

Type RM Length L Ch R = 1 ,7528    ,306.9,306,304.2
XS GIS Cut Line= 4
2295051.30039333673675.1881770762295136.12695721673946.979412355
2295041.81886088674414.0344730632295158.63196395674658.483856305
#Sta/Elev= 30
       0 2079.66    64.9 2056.16    90.1 2042.51   140.4  2021.3   190.6 2004.64
   224.2 1998.58   282.8 1992.75   364.5 1986.39   430.8 1990.62   576.7  1990.9
   588.9 1988.36   625.7 1987.68   680.4 1988.98   688.7 1987.78     695 1986.32
  702.961987.776   707.5 1989.12   723.6 1990.63   739.9 2001.74   752.2 2005.99
   761.2 2004.82   795.7  2007.7   800.2 2008.57     809 2014.03   813.3 2015.02
   857.8 2018.71   884.4 2022.28   902.1 2026.14   966.6 2046.31  1032.1 2064.65
#Mann= 9 ,-1,0
       0      .1       0  374.72     .05       0  674.72     .06       0
   688.7    .045       0  702.96     .06       0   771.2     .05       0
   881.2      .1       0   961.2     .06       0   991.2      .1       0
#XS Ineff= 2 , 0
          598.91 1995.47
Permanent Ineff=
       F       F
Bank Sta=688.7,702.96
XS Rating Curve= 0 ,0
Exp/Cntr(USF)=0,0
Exp/Cntr=0.3,0.1

Type RM Length L Ch R = 1 ,7222    ,34.8,34.4,34.3
XS GIS Cut Line= 3
2294743.92988267674016.0054880892294753.62890302674478.558697072
2295085.18778759 674661.42022861
#Sta/Elev= 30
       0 2050.22    45.2 2023.61    93.2  1998.9   109.2 1987.79   125.2 1981.41
   173.2 1984.43   197.2 1984.13   217.2 1986.03   241.2 1986.29   277.2 1984.97
   289.2 1983.49   305.2  1983.7   309.2 1982.67   313.2 1981.59  317.861982.667
   325.2 1984.11   361.3 1985.09   373.3 1989.33   393.3    1991   405.3 1991.52
   429.3 1989.34   462.7 1991.29   542.6 2003.49   611.7  2010.1   635.6 2014.86
   703.1 2018.79   713.8 2021.01   725.9 2025.42   766.3 2036.82   841.3 2052.71
#Mann= 6 ,-1,0
       0      .1       0     210     .05       0   309.2    .045       0
  317.86     .05       0     410     .06       0  552.65      .1       0
#XS Ineff= 2 , 0
           242.6 1989.82
Permanent Ineff=
       F       F
Bank Sta=309.2,317.86
XS Rating Curve= 0 ,0
Exp/Cntr(USF)=0,0
Exp/Cntr=0.3,0.1

Type RM Length L Ch R = 1 ,7187    ,402.6,402.8,402.2
XS GIS Cut Line= 3
2294700.19896691674017.7630095922294724.93868835674503.568854445
2294821.85340017674890.525566561
#Sta/Elev= 30
       0 2057.22    23.4 2045.26   125.2 1986.85   135.6  1982.9   167.6 1981.06
   179.6 1983.43   211.7 1984.56   239.7 1987.18   287.8 1983.75   299.8 1984.26
  305.521982.752  317.511982.769   399.9 1988.03     432 1988.75     460 1988.29
     484 1989.77   537.6 1986.92   603.6 1988.85   627.2 1994.28   644.8 1996.66
   677.8 2012.17   694.3  2011.7   710.8 2012.95   723.1 2017.04   735.5 2016.58
   739.6 2017.35   756.1 2025.27   772.6 2025.24     785 2030.22   885.3 2048.44
#Mann= 8 ,-1,0
       0      .1       0     210     .06       0  305.52    .045       0
  317.51     .05       0     410     .06       0  526.44      .1       0
  716.44     .05       0  816.44      .1       0
#XS Ineff= 2 , 0
          249.82 1990.77
Permanent Ineff=
       F       F
Bank Sta=305.52,317.51
XS Rating Curve= 0 ,0
Exp/Cntr(USF)=0,0
Exp/Cntr=0.3,0.1

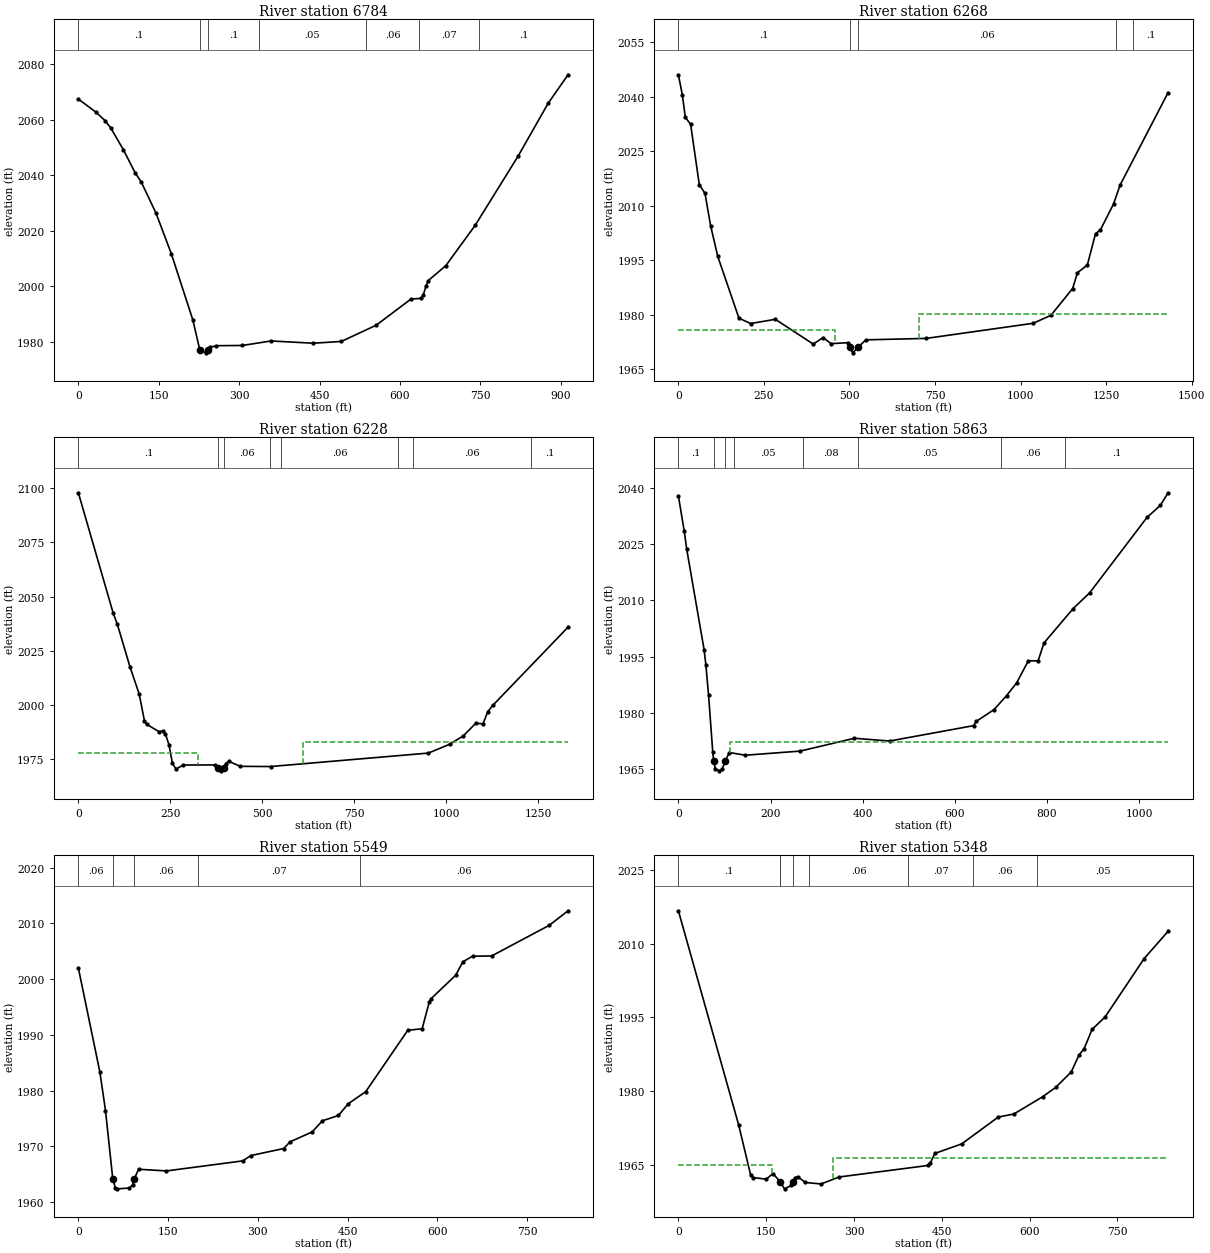
Type RM Length L Ch R = 1 ,6784    ,513.8,516.4,526.9
XS GIS Cut Line= 4
 2294386.8386878674121.177389959 2294313.7455035674198.117583952
2294355.92411785 674727.912371752294494.74538637674966.292327789
#Sta/Elev= 30
       0 2067.45    33.1 2062.69    49.7  2059.7    60.7 2056.97    83.9 2049.23
   106.1 2040.83   117.2 2037.63   144.7 2026.42   173.4 2011.75   213.5 1987.91
   226.4 1977.19   237.6    1976  242.39 1977.19   245.6 1978.01   257.7 1978.58
   305.8 1978.65   359.7 1980.28   438.2 1979.47   490.5  1980.1   555.9 1985.98
   620.4 1995.37   639.1 1995.64   643.7 1996.97   648.3 1999.96   652.9 2002.06
   685.5 2007.42   740.2 2021.93   820.1  2046.8   876.5 2065.96   913.5  2076.2
#Mann= 7 ,-1,0
       0      .1       0   226.4    .045       0  242.39      .1       0
  336.12     .05       0  536.12     .06       0  636.12     .07       0
   747.6      .1       0
Bank Sta=226.4,242.39
XS Rating Curve= 0 ,0
Exp/Cntr(USF)=0,0
Exp/Cntr=0.3,0.1

Type RM Length L Ch R = 1 ,6268    ,41.7,40.1,39.2
XS GIS Cut Line= 4
2293913.30619316673811.8161275222294027.92096114673976.700530585
2293838.90713324674258.2104870352294329.53877162675002.201086222
#Sta/Elev= 30
       0 2046.08    11.7 2040.46    20.3 2034.39    35.8 2032.42    61.1 2015.85
    77.8 2013.42    94.2 2004.55   115.1 1996.09     177  1979.1     211 1977.62
   283.3 1978.79   394.1 1971.97   422.8 1973.77     446 1972.09     495 1972.35
   500.1  1971.1   509.7 1969.56  524.91 1971.11   548.2 1973.14   723.8 1973.53
  1036.7 1977.69  1088.7 1979.88    1152 1987.24  1166.3 1991.61  1195.1 1993.73
    1219 2002.35  1233.4 2003.41  1271.7 2010.52  1290.9 2015.75  1431.1 2041.17
#Mann= 5 ,-1,0
       0      .1       0   500.1    .045       0  524.91     .06       0
 1279.89     .05       0 1329.89      .1       0
#XS Ineff= 2 , 0
          458.63 1975.98  702.37         1980.27
Permanent Ineff=
       F       F
Bank Sta=500.1,524.91
XS Rating Curve= 0 ,0
Exp/Cntr(USF)=0,0
Exp/Cntr=0.3,0.1

Type RM Length L Ch R = 1 ,6228    ,357.4,364.4,337.3
XS GIS Cut Line= 4
2293736.90036328673926.3964826422293904.17131572674092.468483997
2293790.64828356674262.2320578412294281.27992195675006.222657029
#Sta/Elev= 30
       0 2097.99    94.8 2042.31   106.1 2037.14   140.2  2017.6   165.5 2004.87
   179.6 1992.62   185.3 1990.99   219.2 1987.53     231 1987.89   236.6 1986.57
   246.2 1981.58   255.8 1972.83   265.4 1970.25   285.2  1972.1   372.4 1972.16
   380.4 1970.93   386.8 1969.42  396.811970.914   400.2 1972.77   408.4 1973.86
   439.9  1971.5   522.6 1971.41   951.4 1977.63  1008.9 1981.67  1046.6 1985.61
  1080.7 1991.51  1099.9 1991.12    1113  1996.8  1127.5 1999.86  1331.1 2035.86
#Mann= 8 ,-1,0
       0      .1       0   380.4    .045       0  396.81     .06       0
  519.93     .07       0  549.93     .06       0  869.93     .05       0
  909.93     .06       0 1229.93      .1       0
#XS Ineff= 2 , 0
          325.49 1977.81  609.47         1982.77
Permanent Ineff=
       F       F
Bank Sta=380.4,396.81
XS Rating Curve= 0 ,0
Exp/Cntr(USF)=0,0
Exp/Cntr=0.3,0.1

Type RM Length L Ch R = 1 ,5863    ,313.5,314.7,314.4
XS GIS Cut Line= 2
2293471.47231999674340.3848881992294196.63364838675117.480847529
#Sta/Elev= 30
       0 2037.82    12.8 2028.39      18 2023.69    55.8 1996.88    59.7 1992.75
    65.5 1984.77    74.6 1969.61   76.531967.146    80.3 1965.15    88.8 1964.59
    94.8 1964.97  101.851967.239   110.5 1969.47   145.4 1968.75   264.3 1969.85
   382.1 1973.27   458.3 1972.53   640.7 1976.63   646.3 1977.75     685 1980.89
   712.3 1984.62   734.1    1988   759.5 1993.89   780.8 1993.89   793.5 1998.66
     857 2007.83   892.9 2012.04  1017.1 2032.09  1046.1  2035.3  1062.9 2038.66
#Mann= 8 ,-1,0
       0      .1       0   76.53    .045       0  101.85      .1       0
     120     .05       0     270     .08       0     390     .05       0
     700     .06       0     840      .1       0
#XS Ineff= 2 , 0
                          111.48         1972.37
Permanent Ineff=
       F       F
Bank Sta=76.53,101.85
XS Rating Curve= 0 ,0
Exp/Cntr(USF)=0,0
Exp/Cntr=0.3,0.1

Type RM Length L Ch R = 1 ,5549    ,194.2,200.8,203.3
XS GIS Cut Line= 3
2293258.80192977674570.4687678212293580.79664163674927.086566979
2293599.83933965675264.661668124
#Sta/Elev= 30
       0 2002.01      36 1983.35    45.4 1976.44    57.5 1964.25    61.7 1962.65
    65.2 1962.41      85 1962.55    90.7  1963.1   93.691964.238   100.7 1965.92
   147.3 1965.62   274.8 1967.42   288.5 1968.38   343.2 1969.63     354 1970.84
   390.9 1972.61   407.9  1974.6   434.8 1975.56     451 1977.64   480.5 1979.84
   550.7 1990.83   574.7  1991.1   586.7 1995.93   589.5 1996.48   630.8  2000.7
   642.8 2003.11   658.9 2004.11   690.9 2004.15   787.1 2009.64   818.6 2012.25
#Mann= 5 ,-1,0
       0     .06       0    57.5    .045       0   93.69     .06       0
     200     .07       0     470     .06       0
Bank Sta=57.5,93.69
XS Rating Curve= 0 ,0
Exp/Cntr(USF)=0,0
Exp/Cntr=0.3,0.1

Type RM Length L Ch R = 1 ,5348    ,317.3,327.5,337.8
XS GIS Cut Line= 3
2293134.57639794674551.315076291 2293115.2676215674672.846786821
2293428.63910724675313.892555664
#Sta/Elev= 30
       0 2016.65   103.1 1973.12   123.4 1963.03   127.9 1962.49   150.1 1962.16
   161.6 1963.31   174.1  1961.6   181.3  1960.2   192.8 1960.88  196.351961.608
   199.1 1962.47   203.6 1962.68   216.9 1961.49   243.7 1961.19   274.8 1962.61
   426.2 1964.94   430.6 1965.47     438 1967.38   484.1 1969.33   546.4 1974.77
   573.1 1975.39   622.1 1978.88   644.4 1980.78   671.1 1983.92   684.4 1987.35
   693.3 1988.68   706.7 1992.56   728.9 1995.08   795.7 2006.95   836.6 2012.48
#Mann= 8 ,-1,0
       0      .1       0  173.06     .05       0   174.1    .045       0
  196.35     .05       0  223.06     .06       0  393.06     .07       0
  503.06     .06       0  613.06     .05       0
#XS Ineff= 2 , 0
          159.57 1965.06  264.12          1966.4
Permanent Ineff=
       F       F
Bank Sta=174.1,196.35
XS Rating Curve= 0 ,0
Exp/Cntr(USF)=0,0
Exp/Cntr=0.3,0.1