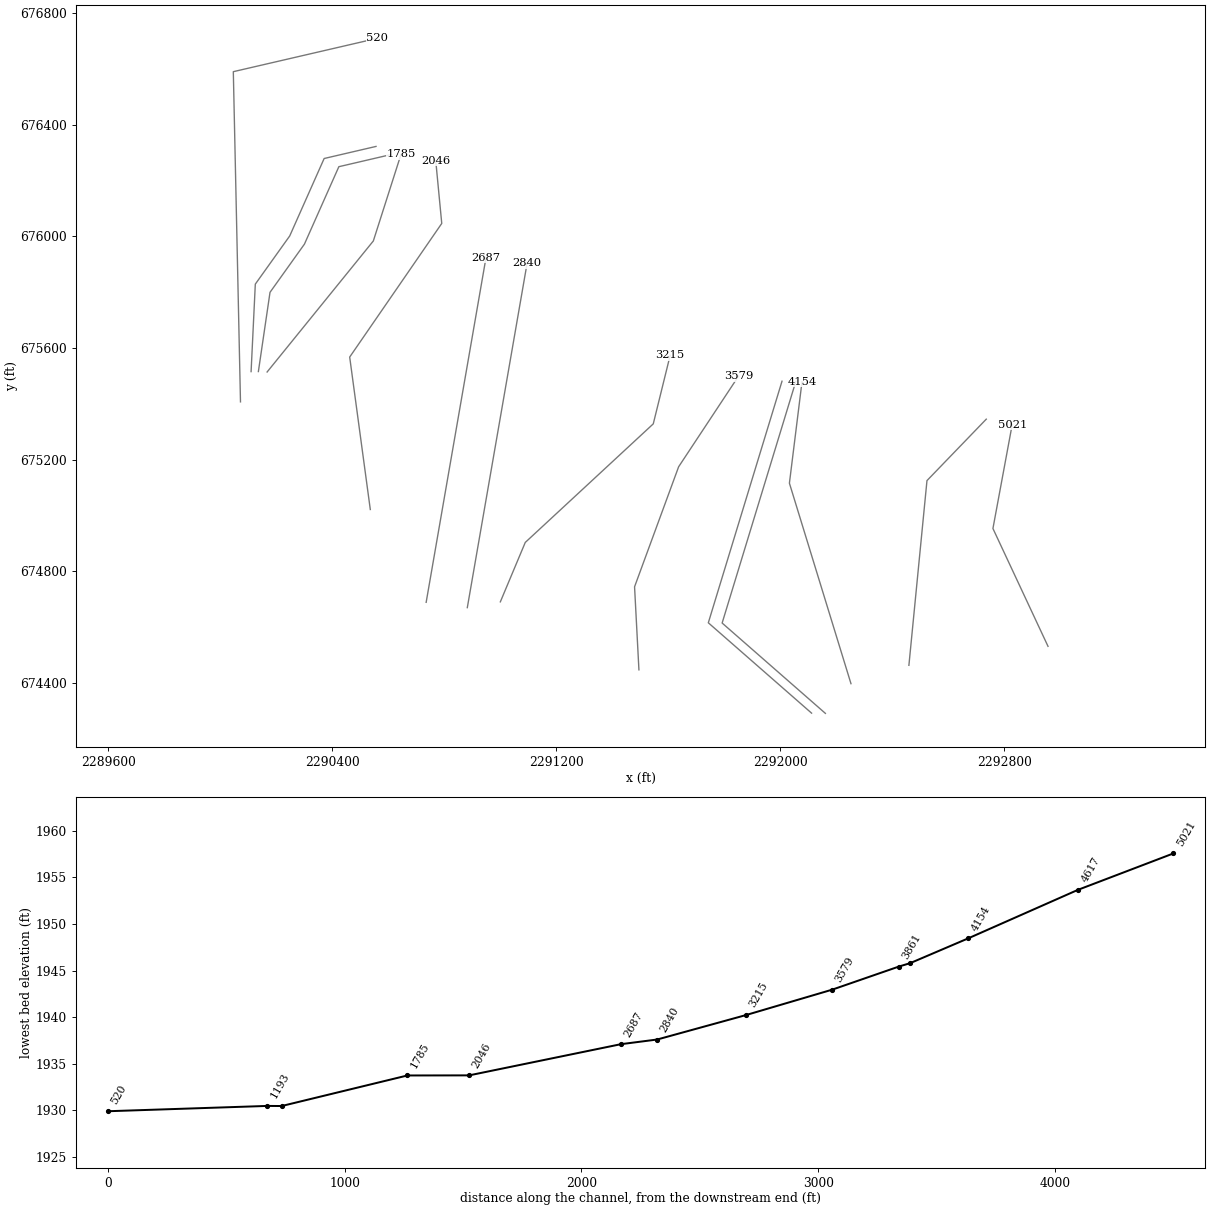
HEC-RAS study DODSONRN.prj: DODSONRN

--- DODSONRN.g01 (geometry) --- (continued)

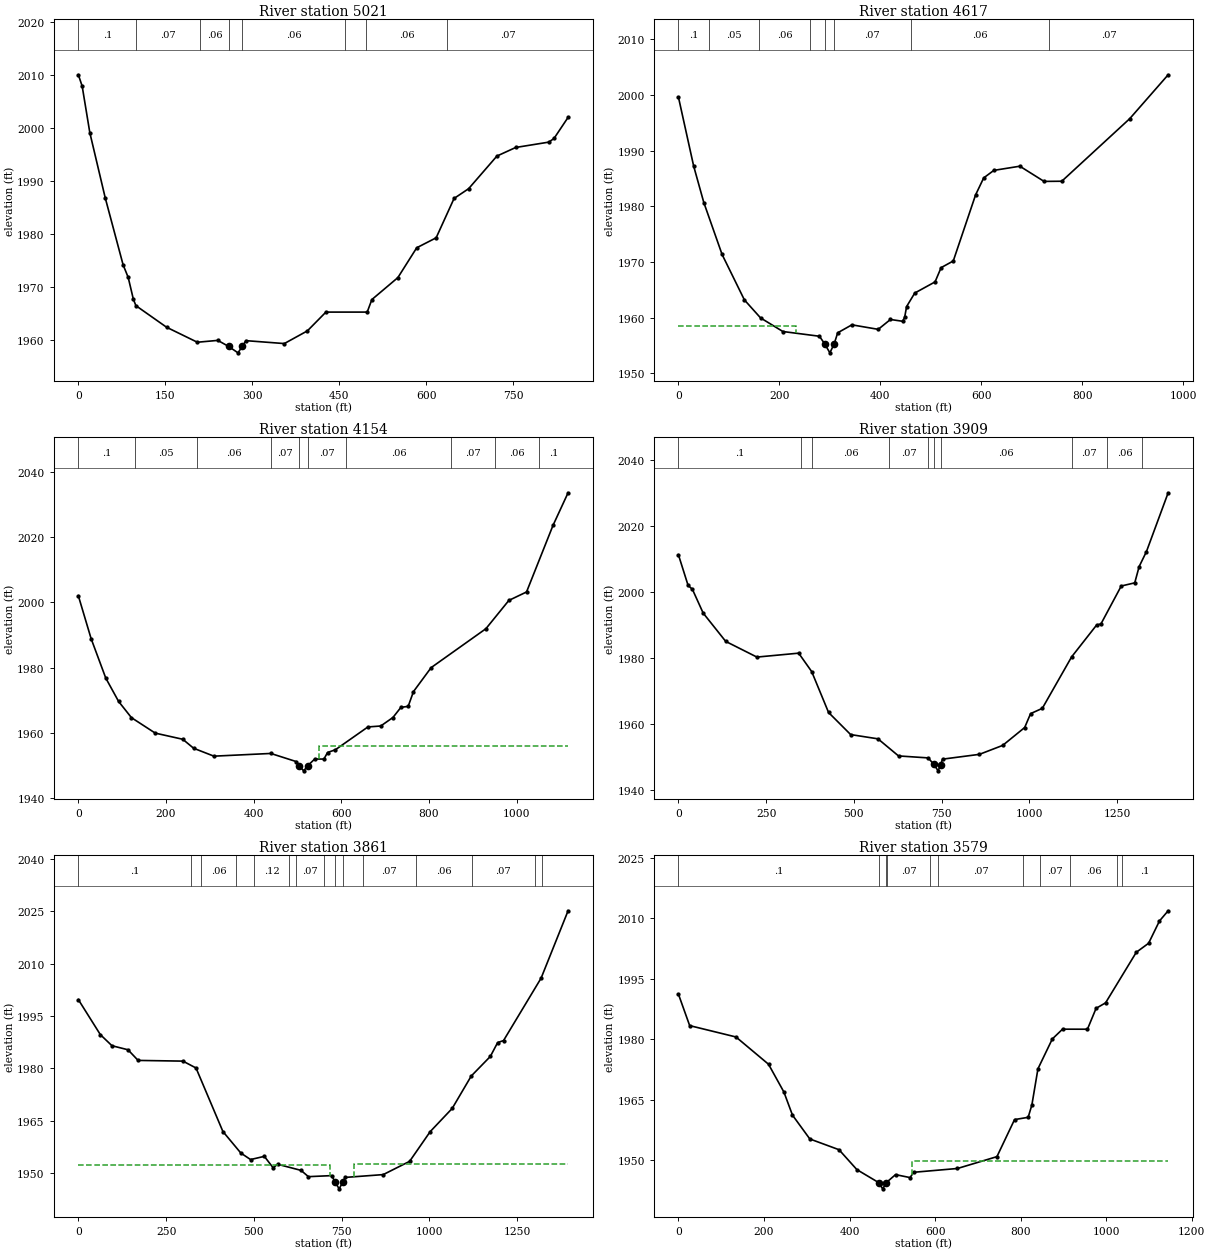
Type RM Length L Ch R = 1 ,5021    ,406.7,403.2,396.1
XS GIS Cut Line= 3
2292956.47681703674531.1950613692292759.75882193674953.335322082
2292828.56874563675325.760291746
#Sta/Elev= 30
       0 2010.06     6.6 2007.92    19.8 1999.13    46.3 1986.86    77.2 1974.19
      86 1971.81    94.9 1967.68    99.3 1966.48   152.2 1962.41   205.2 1959.58
   240.5 1959.93  259.221958.784   275.3 1957.58   282.6 1958.78     289 1959.88
   355.2 1959.33   394.9 1961.72   426.9 1965.27   498.1 1965.27   506.2 1967.64
     551 1971.78   583.5 1977.41     617 1979.29   647.9 1986.72     673 1988.56
   721.8 1994.72   754.2 1996.34   811.3 1997.35   820.3 1998.05   844.5 2002.02
#Mann= 8 ,-1,0
       0      .1       0     100     .07       0     210     .06       0
  259.22    .045       0   282.6     .06       0     460     .07       0
  495.73     .06       0  635.73     .07       0
Bank Sta=259.22,282.6
XS Rating Curve= 0 ,0
Exp/Cntr(USF)=0,0
Exp/Cntr=0.3,0.1

Type RM Length L Ch R = 1 ,4617    ,461.7,463.6,469.5
XS GIS Cut Line= 3
2292459.71213155674463.1078839362292524.21494318675124.962820704
2292735.95243355675345.113721282
#Sta/Elev= 30
       0 1999.61    30.2 1987.21    50.3 1980.67    86.5 1971.34   130.7 1963.18
   162.8 1959.94     207  1957.5   279.4 1956.65  289.591955.319   300.1 1953.67
  308.661955.294   315.6 1957.27   343.7  1958.7   395.9 1957.89   420.1 1959.66
   444.2 1959.34   448.2 1960.03   452.2 1961.99   468.3 1964.41   508.5 1966.41
   520.5 1968.97   544.6 1970.17   588.8 1982.03   604.9 1985.09     625 1986.44
   676.5 1987.19   724.5 1984.46   759.6 1984.49   894.3 1995.73   970.4 2003.61
#Mann= 8 ,-1,0
       0      .1       0      60     .05       0     160     .06       0
     260     .07       0  289.59    .045       0  308.66     .07       0
     460     .06       0  734.99     .07       0
#XS Ineff= 2 , 0
          233.94 1958.43
Permanent Ineff=
       F       F
Bank Sta=289.59,308.66
XS Rating Curve= 0 ,0
Exp/Cntr(USF)=0,0
Exp/Cntr=0.3,0.1

Type RM Length L Ch R = 1 ,4154    ,250.2,245,238.6
XS GIS Cut Line= 3
2292252.84239079674397.3282925272292032.98578646675115.757353939
2292077.99579994675479.299770556
#Sta/Elev= 30
       0 2002.03    29.1 1988.93    62.6 1976.84    91.9 1969.69   121.2 1964.73
   175.5    1960   238.3 1958.12   263.1 1955.37   309.4 1952.95   439.2 1953.78
   497.6 1951.28  503.721950.004   514.4 1948.46  523.431950.044   539.5 1952.08
   560.4 1952.06   568.7 1954.07   586.6 1954.91   660.8 1961.89   690.1 1962.18
   717.9 1964.78   736.1 1967.88   752.7 1968.19   764.8 1972.71   805.1 1980.04
   930.1 1991.95   982.5 2000.61  1022.8 2003.19  1083.3 2023.59  1117.6 2033.54
#Mann= 10 ,-1,0
       0      .1       0     130     .05       0     270     .06       0
     440     .07       0  503.72    .045       0  523.43     .07       0
     610     .06       0  851.32     .07       0  951.32     .06       0
 1051.32      .1       0
#XS Ineff= 2 , 0
                          550.18         1956.12
Permanent Ineff=
       F       F
Bank Sta=503.72,523.43
XS Rating Curve= 0 ,0
Exp/Cntr(USF)=0,0
Exp/Cntr=0.3,0.1

Type RM Length L Ch R = 1 ,3909    ,48.5,48.1,48
XS GIS Cut Line= 3
2292161.47591043674290.9371020552291792.74003071674614.662968282
2292055.87549417675480.240150705
#Sta/Elev= 30
       0 2011.29    27.6 2001.99    39.8 2000.83    70.5 1993.62   134.8 1985.03
   223.6 1980.28   342.6 1981.47   379.7 1975.89   427.8 1963.49   490.7 1956.79
   568.6  1955.5   627.1 1950.32   711.6 1949.72  727.511947.789     740  1945.8
   747.21947.714   752.5 1949.34   857.7  1950.8   923.9 1953.51   986.6 1958.93
  1003.4 1963.14  1036.8 1964.74  1120.4 1980.35  1191.5 1989.99  1203.9 1990.33
  1261.7 2001.82  1300.2 2002.78  1312.7 2007.71  1333.6 2012.27  1395.4 2030.08
#Mann= 10 ,-1,0
       0      .1       0     350     .05       0     380     .06       0
  600.68     .07       0  710.68     .06       0  727.51    .045       0
   747.2     .06       0 1120.68     .07       0 1220.68     .06       0
 1320.68      .1       0
Bank Sta=727.51,747.2
XS Rating Curve= 0 ,0
Exp/Cntr(USF)=0,0
Exp/Cntr=0.3,0.1

Type RM Length L Ch R = 1 ,3861    ,282,281.6,281.4
XS GIS Cut Line= 3
2292112.13801103674291.8026792382291743.40213132674615.528545464
2292006.53759477675481.105727888
#Sta/Elev= 30
       0 1999.66    62.7 1989.62    95.8 1986.44   141.5 1985.28   170.3 1982.23
     298 1982.03   335.3 1980.06   411.9 1961.86     463 1955.69   490.7 1953.82
     530 1954.74   555.1 1951.45   567.7 1952.48   634.5 1950.72   655.5 1948.92
   722.3 1949.22  731.111947.399   743.2 1945.43  753.431947.362     760  1948.7
   868.7 1949.51   943.9 1953.31  1002.5 1961.82  1065.2 1968.47  1119.5 1977.76
  1173.9 1983.37  1194.7 1987.34  1211.5 1987.92  1318.5  2005.8  1395.4 2025.11
#Mann= 15 ,-1,0
       0      .1       0     320     .12       0     350     .06       0
     450      .1       0  500.68     .12       0  600.68     .06       0
  620.68     .07       0  700.68     .06       0  731.11    .045       0
  753.43     .06       0  810.68     .07       0  960.68     .06       0
 1120.68     .07       0 1300.68     .06       0 1320.68      .1       0
#XS Ineff= 2 , 0
          716.68 1952.13  785.42         1952.43
Permanent Ineff=
       F       F
Bank Sta=731.11,753.43
XS Rating Curve= 0 ,0
Exp/Cntr(USF)=0,0
Exp/Cntr=0.3,0.1

Type RM Length L Ch R = 1 ,3579    ,369.6,364.5,358.7
XS GIS Cut Line= 4
2291495.58911514674446.9019922472291480.00872586674744.487427565
2291637.37065762675174.5061717932291851.32210207675499.328435784
#Sta/Elev= 30
       0 1991.17    26.3 1983.37   134.5 1980.56   210.6 1973.81   246.6 1966.92
   266.6 1961.21   307.2  1955.3   375.4 1952.64   417.2 1947.71  467.93 1944.51
   477.6 1942.95   486.1 1944.51   507.6 1946.47   541.5 1945.74     550 1947.05
   652.3 1947.99   744.6 1950.92   785.8  1960.1   817.6 1960.66   826.3 1963.72
   840.5 1972.68   874.1 1980.07     898 1982.49   956.2 1982.48   976.4 1987.65
   998.6 1989.01  1070.4 2001.53  1099.2 2003.77  1124.6 2009.29  1144.9 2011.81
#Mann= 11 ,-1,0
       0      .1       0  467.93    .045       0   486.1      .1       0
  487.99     .07       0  587.99     .08       0  607.99     .07       0
   805.9     .08       0   845.9     .07       0   915.9     .06       0
  1025.9     .07       0  1035.9      .1       0
#XS Ineff= 2 , 0
                          545.85         1949.82
Permanent Ineff=
       F       F
Bank Sta=467.93,486.1
XS Rating Curve= 0 ,0
Exp/Cntr(USF)=0,0
Exp/Cntr=0.3,0.1

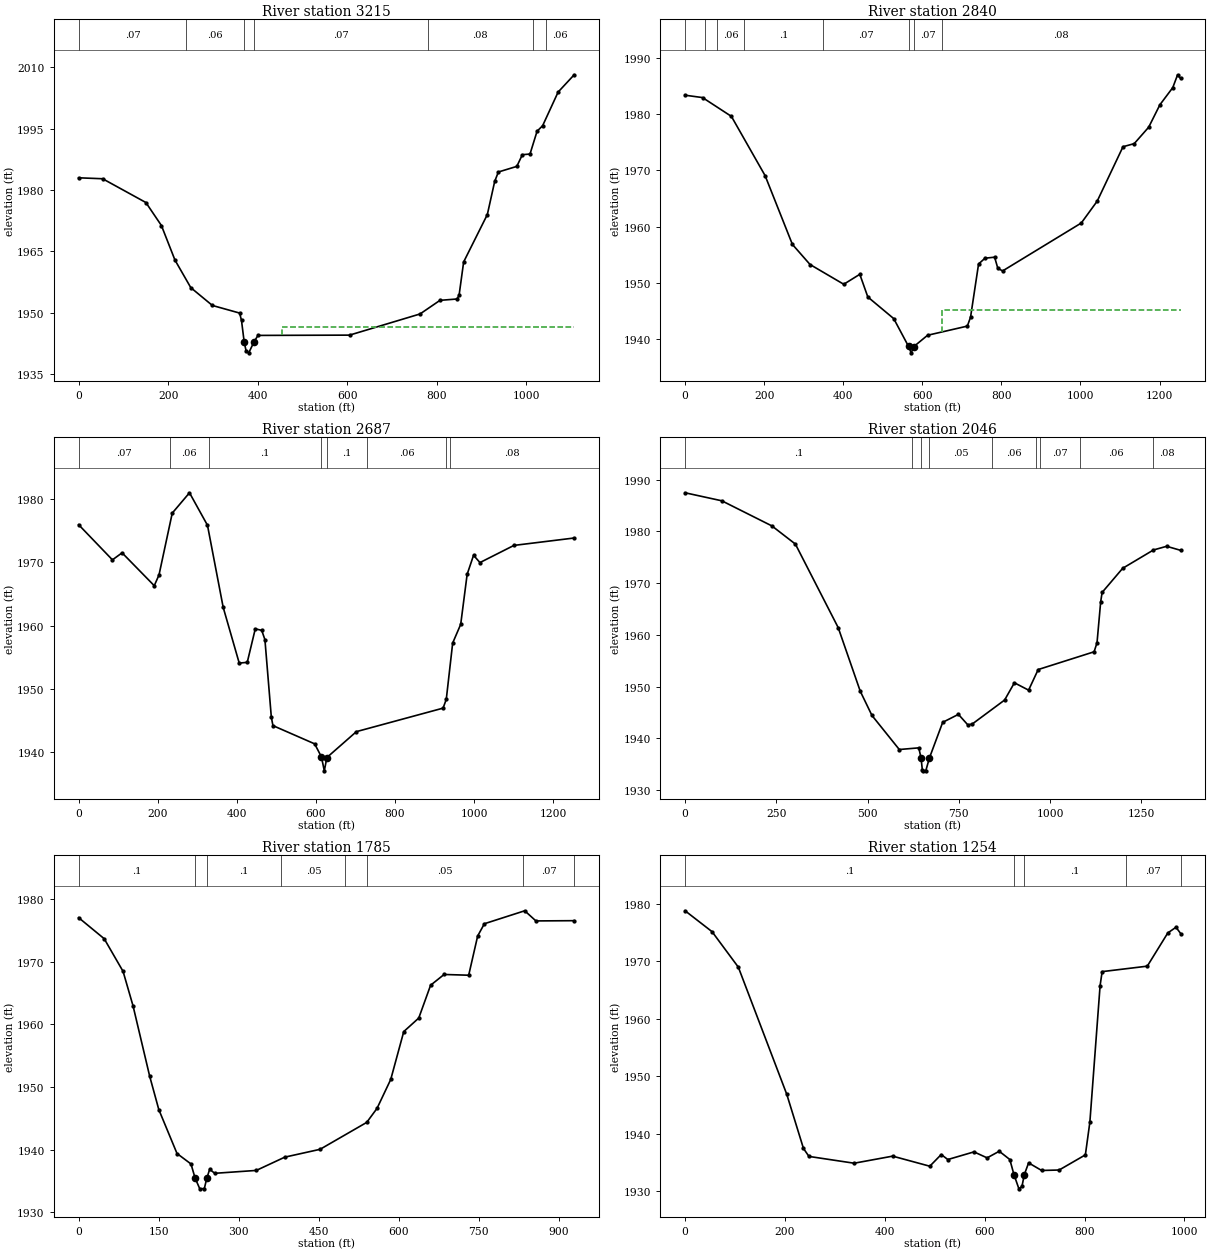
Type RM Length L Ch R = 1 ,3215    ,367.9,374.4,377
XS GIS Cut Line= 4
2291000.69055233674690.5138814782291089.68727472674903.422786297
 2291546.8158963675328.3000020612291607.11200283675573.691133279
#Sta/Elev= 30
       0    1983    53.6 1982.77   150.3 1976.96     185 1971.34   215.3 1962.89
   250.7 1956.15   298.9  1951.8   359.8 1949.94     364 1948.13  369.991942.881
   374.4 1940.62   380.2 1940.22  391.931942.891   400.8 1944.48   605.5 1944.55
     763 1949.72   807.6 1953.05   845.8 1953.38   850.3  1954.3   860.5 1962.44
   913.4 1974.01   929.9 1982.13   938.1 1984.42   979.3 1985.79   991.7 1988.65
  1008.8 1988.81  1024.6 1994.39    1037 1995.73  1071.6 2003.95  1107.5 2008.18
#Mann= 7 ,-1,0
       0     .07       0  240.76     .06       0  369.99    .045       0
  391.93     .07       0  780.76     .08       0 1014.85     .07       0
 1044.85     .06       0
#XS Ineff= 2 , 0
                          454.01         1946.42
Permanent Ineff=
       F       F
Bank Sta=369.99,391.93
XS Rating Curve= 0 ,0
Exp/Cntr(USF)=0,0
Exp/Cntr=0.3,0.1

Type RM Length L Ch R = 1 ,2840    ,154.1,152.9,154.2
XS GIS Cut Line= 2
2290882.72268855674669.7699740342291096.44544964 675904.82631644
#Sta/Elev= 30
       0 1983.36    44.1 1982.94   117.1  1979.6   202.4 1969.07   271.4 1956.86
     316 1953.29   401.3 1949.78   441.9 1951.55   462.2 1947.52   527.7 1943.68
  565.151938.746   571.8  1937.6  578.631938.721   613.3 1940.72   713.9 1942.35
     722 1943.93   742.3 1953.38   758.5 1954.41   782.9 1954.59     791 1952.61
   803.2 1952.15  1002.1 1960.66  1042.4 1964.55  1107.6 1974.21    1136 1974.76
  1172.6 1977.68    1201 1981.67  1233.5 1984.71  1245.7 1986.99  1253.4 1986.33
#Mann= 8 ,-1,0
       0     .05       0      50     .07       0      80     .06       0
     150      .1       0     350     .07       0  565.15    .045       0
  578.63     .07       0     650     .08       0
#XS Ineff= 2 , 0
                          650.97         1945.27
Permanent Ineff=
       F       F
Bank Sta=565.15,578.63
XS Rating Curve= 0 ,0
Exp/Cntr(USF)=0,0
Exp/Cntr=0.3,0.1

Type RM Length L Ch R = 1 ,2687    ,636.8,641.4,622.2
XS GIS Cut Line= 2
2290735.78923849674688.8977852062290949.51199959675923.954127613
#Sta/Elev= 30
       0 1975.96    85.5 1970.41   109.9 1971.52   191.3 1966.33   203.3 1968.03
   236.8 1977.79   280.4    1981   325.9 1975.87   365.6 1962.92   406.2 1954.11
   426.5 1954.23   446.8 1959.52   463.1 1959.28   471.2 1957.81   487.4 1945.57
   491.5 1944.24     597 1941.36  614.171939.299   621.4  1937.1  627.911939.203
   702.6 1943.29   921.8    1947   929.9 1948.38   946.1 1957.28   966.4 1960.23
   982.7 1968.13   998.9 1971.13  1015.1 1969.98    1101 1972.69  1253.4 1973.86
#Mann= 8 ,-1,0
       0     .07       0     230     .06       0     330      .1       0
  614.17    .045       0  627.91      .1       0     730     .06       0
     930     .07       0     940     .08       0
Bank Sta=614.17,627.91
XS Rating Curve= 0 ,0
Exp/Cntr(USF)=0,0
Exp/Cntr=0.3,0.1

Type RM Length L Ch R = 1 ,2046    ,261.3,260.6,259.4
XS GIS Cut Line= 4
2290536.31466147675021.4622749532290462.69904376675567.642664411
2290791.46665156676046.452397857 2290769.9998354676271.342852855
#Sta/Elev= 30
       0 1987.47   100.6 1985.92   237.8 1981.07   302.2 1977.56   419.5 1961.42
     480 1949.12     512 1944.45   586.9 1937.87   640.3 1938.19  646.481936.249
     650 1933.98   652.7 1933.75   659.7 1933.81   669.4 1936.23   705.8 1943.12
   748.9 1944.66   774.8 1942.62   786.9  1942.8   875.5 1947.43   902.3 1950.76
   941.2 1949.34   967.5 1953.32  1120.7 1956.75  1128.7 1958.51  1138.7 1966.41
  1142.7 1968.22    1199 1972.88  1283.3 1976.42  1319.5 1977.13  1357.8 1976.35
#Mann= 9 ,-1,0
       0      .1       0  621.12     .05       0  646.48    .045       0
   669.4     .05       0  841.12     .06       0  961.12     .05       0
  971.12     .07       0 1081.12     .06       0 1281.93     .08       0
Bank Sta=646.48,669.4
XS Rating Curve= 0 ,0
Exp/Cntr(USF)=0,0
Exp/Cntr=0.3,0.1

Type RM Length L Ch R = 1 ,1785    ,522.6,530.9,527.3
XS GIS Cut Line= 3
2290167.83466834675514.1402096212290547.16036554675983.658876108
2290645.83616433676293.535507416
#Sta/Elev= 30
       0 1977.04    47.9 1973.68    83.3 1968.46     102 1962.95   133.2 1951.71
   150.3 1946.39   184.4 1939.38   210.6 1937.71  218.151935.496   227.1 1933.74
   235.6 1933.79  240.151935.397   245.6 1936.86   255.1 1936.22     333 1936.68
   386.4  1938.8   452.5 1940.05     540 1944.35   559.3 1946.59     585 1951.21
   609.4 1958.85   637.5 1961.01   659.7 1966.25     685 1967.97   731.1 1967.85
   747.9 1974.11   760.5 1976.07   836.1 1978.14   857.1 1976.52   928.8 1976.56
#Mann= 8 ,-1,0
       0      .1       0  218.15    .045       0  240.15      .1       0
     380     .05       0     500     .07       0     540     .05       0
   833.6     .07       0  928.81     .06       0
Bank Sta=218.15,240.15
XS Rating Curve= 0 ,0
Exp/Cntr(USF)=0,0
Exp/Cntr=0.3,0.1

Type RM Length L Ch R = 1 ,1254    ,60.9,61.1,61.2
XS GIS Cut Line= 5
2290136.64999987675515.7348896012290178.19770463675799.644205437
2290301.13130396675972.3505701452290424.02162444676249.744340298
2290609.25514147676293.023199419
#Sta/Elev= 30
       0 1978.76      54 1975.13   106.6 1968.97   203.6 1946.89   237.1 1937.47
   248.1 1936.09   338.6 1934.91   415.7 1936.14   490.1 1934.39     513 1936.42
   526.2 1935.55   578.6 1936.88   604.9 1935.84   629.2 1936.99   650.4 1935.55
   658.61932.945   668.6 1930.46   674.7 1930.88  679.391932.922     688 1934.97
   714.1 1933.65   749.2 1933.73   801.7 1936.36   810.7 1942.05   831.2 1965.78
   835.3 1968.19   925.7 1969.14   966.8 1974.91   983.2  1975.9   992.5 1974.81
#Mann= 5 ,-1,0
       0      .1       0   658.6    .045       0  679.39      .1       0
  882.32     .07       0  992.32     .06       0
Bank Sta=658.6,679.39
XS Rating Curve= 0 ,0
Exp/Cntr(USF)=0,0
Exp/Cntr=0.3,0.1

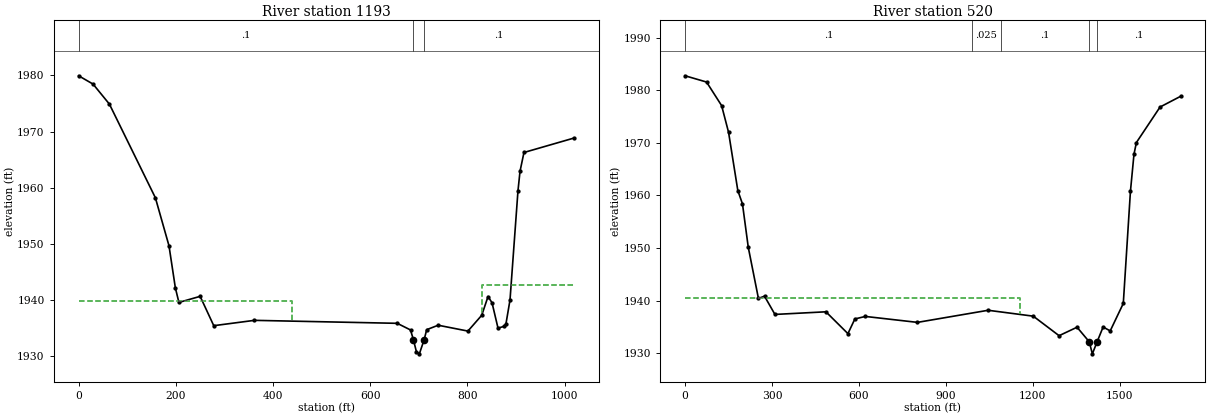
Type RM Length L Ch R = 1 ,1193    ,674.2,673,654
XS GIS Cut Line= 5
2290110.62417138675515.4861227192290125.68521435675828.998178193
2290248.61881369676001.7045429022290371.50913416676279.098313055
 2290556.7426512676322.377172176
#Sta/Elev= 30
       0 1979.95    29.7 1978.47    63.3 1974.91   157.9 1958.24   185.9  1949.7
     199 1942.21   206.3 1939.62     250  1940.7     278 1935.48   361.7 1936.43
   655.5  1935.9   682.8 1934.72   688.8 1932.97   694.9 1930.85     701 1930.47
  710.761932.959   716.1 1934.77   739.7 1935.56   800.9 1934.52   829.3 1937.33
   842.3 1940.67   850.5 1939.56   862.8 1935.05   875.6 1935.37   879.2 1935.83
   887.5 1940.06   903.9  1959.5   908.1 1962.96   916.2  1966.3  1019.5 1968.88
#Mann= 3 ,-1,0
       0      .1       0   688.8    .045       0  710.76      .1       0
#XS Ineff= 2 , 0
          439.34 1939.87   830.6         1942.67
Permanent Ineff=
       F       F
Bank Sta=688.8,710.76
XS Rating Curve= 0 ,0
Exp/Cntr(USF)=0,0
Exp/Cntr=0.3,0.1

Type RM Length L Ch R = 1 ,520     ,,,
XS GIS Cut Line= 3
2290072.74720541675407.0851461012290047.13820116676590.221142551
2290561.01060603676709.683843826
#Sta/Elev= 30
       0 1982.75    74.1 1981.56   126.1 1977.08   150.1    1972   182.1 1960.92
   198.1  1958.4   218.1 1950.16   253.2 1940.43   274.2 1940.86   310.2 1937.39
   486.2 1937.89   562.2 1933.74   586.2 1936.53   622.2 1937.01   802.3 1935.88
  1046.3 1938.18  1202.2 1937.06  1291.3 1933.35  1353.3 1934.96 1395.411932.193
  1406.2  1929.9  1422.7  1932.2  1443.3    1935  1467.8 1934.26    1513 1939.48
  1537.7 1960.81  1549.9 1967.83  1558.2 1970.06  1639.9 1976.81    1711 1978.85
#Mann= 5 ,-1,0
       0      .1       0     990    .025       0    1090      .1       0
 1395.41    .045       0  1422.7      .1       0
#XS Ineff= 2 , 0
         1157.38 1940.53
Permanent Ineff=
       F       F
Bank Sta=1395.41,1422.7
XS Rating Curve= 0 ,0
Exp/Cntr(USF)=0,0
Exp/Cntr=0.3,0.1
LCMann Table=0

Chan Stop Cuts=-1
Use User Specified Reach Order=0
Composite Channel Slope=5